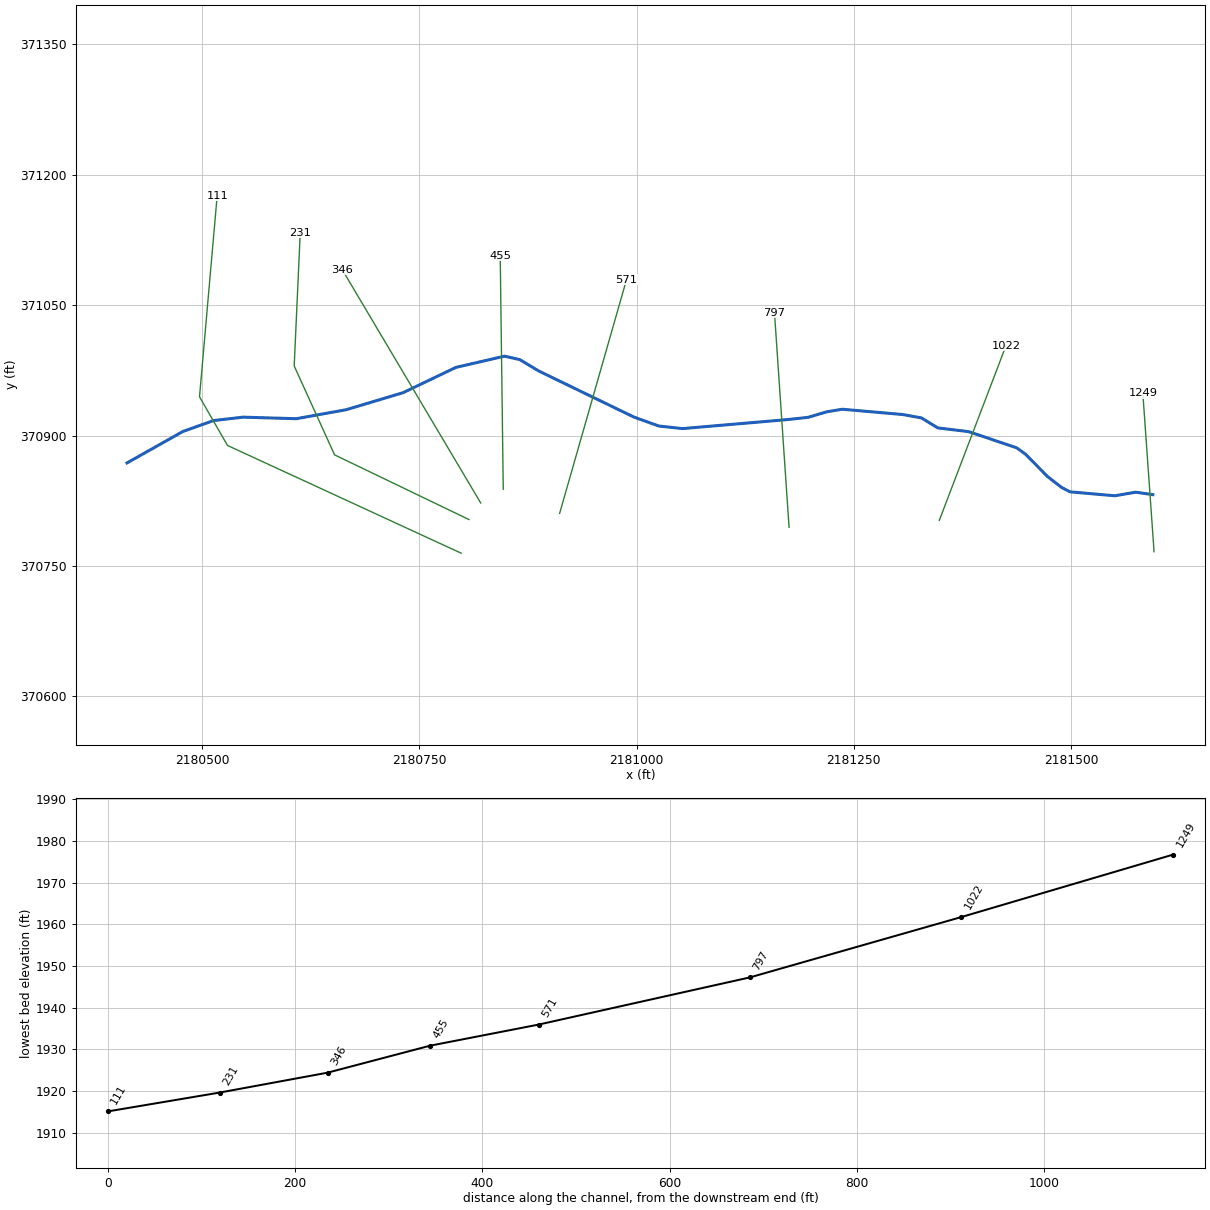
--- KINCAIDRN.prj (project) ---

Proj Title=KINCAIDRN
Current Plan=p01
Default Exp/Contr=0,0
English Units
Geom File=g02
Flow File=f01
Plan File=p01
BEGIN DESCRIPTION:
Stream Name- Kincaid Run
Flood Zone: Zone A
Greenbrier County, WV
County-Wide Study
WVDHSEM-2018-3, Flood Risk Project
HEC-RAS Version: 5.0.7
General Notes:
For the Hydrology Regression was used.
END DESCRIPTION:
DSS Export Rating Curves= 0
DSS Export Rating Curve Sorted= 0
DSS Export Volume Flow Curves= 0
DXF OffsetX= 0
DXF OffsetY= 0
DXF ScaleX= 0
DXF ScaleY= 0

--- KINCAIDRN.p01 (plan) ---

Plan Title=Floodplain
Program Version=5.07
Short Identifier=Floodplain
Geom File=g02
Flow File=f01
Subcritical Flow
K Sum by GR= 0
Std Step Tol= 0.01
Critical Tol= 0.01
Num of Std Step Trials= 20
Max Error Tol= 0.3
Flow Tol Ratio= 0.001
Split Flow NTrial= 30
Split Flow Tol= 0.02
Split Flow Ratio= 0.02
Log Output Level= 0
Friction Slope Method= 1
Unsteady Friction Slope Method= 2
Unsteady Bridges Friction Slope Method= 1
Parabolic Critical Depth
Global Vel Dist= 0 , 0 , 0
Global Log Level= 0
CheckData=True
Encroach Param=-1 ,0,0, 0
Mapping Interval=1HOUR
Computation Time Step Use Courant=        0
Computation Time Step Use Time Series=    0
Computation Time Step Count To Double=0
Computation Time Step Max Doubling=0
Computation Time Step Max Halving=0
Computation Time Step Residence Courant=0
Run HTab= 0
Run UNet= 0
Run Sediment= 0
Run PostProcess= 0
Run WQNet= 0
Run RASMapper=-1
UNET Theta= 0
UNET Theta Warmup= 0
UNET ZTol= 0
UNET ZSATol= 0
UNET MxIter= 0
UNET Max Iter WO Improvement= 0
UNET MaxInSteps= 0
UNET DtIC= 0
UNET DtMin= 0
UNET MaxCRTS= 0
UNET WFStab= 0
UNET SFStab= 0
UNET WFX= 1
UNET SFX= 1
UNET 1D Methodology=Finite Difference
UNET DSS MLevel= 1
UNET Pardiso=0
UNET DZMax Abort= 0
UNET Use Existing IB Tables= 0
UNET Froude Reduction=False
UNET Froude Limit= 0
UNET Froude Power= 0
UNET D1 Cores= 0
UNET D2 Coriolis=0
UNET D2 Cores= 0
UNET D2 Theta= 1
UNET D2 Theta Warmup= 1
UNET D2 Z Tol= 0.01
UNET D2 Volume Tol= 0.01
UNET D2 Max Iterations= 20
UNET D2 Equation= 0
UNET D2 RampUpFraction=0.1
UNET D2 TimeSlices= 1
UNET D2 BCVolumeCheck=0
UNET D1D2 MaxIter= 0
UNET D1D2 ZTol=0.01
UNET D1D2 QTol=0.1
UNET D1D2 MinQTol=1
Write IC File= 0
Write IC File at Fixed DateTime=0
Write IC File at Sim End=0
Echo Input=False
Echo Parameters=False
Echo Output=False
Write Detailed= 0
HDF Write Warmup=0
HDF Write Time Slices=0
HDF Flush=0
HDF Face Node Velocities=0
HDF Compression= 1
HDF Chunk Size= 1
HDF Spatial Parts= 1
HDF Use Max Rows=0
HDF Fixed Rows= 1
Calibration Method= 0
Calibration Iterations= 20
Calibration Max Change=0.05
Calibration Tolerance=0.2
Calibration Maximum=1.5
Calibration Minimum=0.5
Calibration Optimization Method= 1
WQ AD Non Conservative
WQ ULTIMATE=-1
WQ Max Comp Step=1HOUR
WQ Output Interval=15MIN
WQ Output Selected Increments= 0
WQ Output face flow=0
WQ Output face velocity=0
WQ Output face area=0
WQ Output face dispersion=0
WQ Output cell volume=0
WQ Output cell surface area=0
WQ Output cell continuity=0
WQ Output cumulative cell continuity=0
WQ Output face conc=0
WQ Output face dconc_dx=0
WQ Output face courant=0
WQ Output face peclet=0
WQ Output face adv mass=0
WQ Output face disp mass=0
WQ Output cell mass=0
WQ Output cell source sink temp=0
WQ Output nsm pathways=0
WQ Output nsm derived pathways=0
WQ Output MaxMinRange=-1
WQ Daily Max Min Mean=-1
WQ Daily Range=0
WQ Daily Time=0
WQ Create Restart=0
WQ Fixed Restart=0
WQ System Summary=0
WQ Write To DSS=0
WQ Use Fixed Temperature=0
Sorting and Armoring Iterations= 10
XS Update Threshold= 0.02
Bed Roughness Predictor= 0
Hydraulics Update Threshold= 0.02
Energy Slope Method= 1
Volume Change Method= 1
Sediment Retention Method= 0
XS Weighting Method= 0
Number of US Weighted Cross Sections= 1
Number of DS Weighted Cross Sections= 1
Upstream XS Weight=0
Main XS Weight=1
Downstream XS Weight=0
Number of DS XS's Weighted with US Boundary= 1
Upstream Boundary Weight= 1
Weight of XSs Associated with US Boundary= 0
Number of US XS's Weighted with DS Boundary= 1
Downstream Boundary Weight= 0.5
Weight of XSs Associated with DS Boundary= 0.5
Percentile Method= 0
Sediment Output Level= 3
Mass or Volume Output= 0
Output Increment Type= 1
Profile and TS Output Increment= 1
XS Output Flag= 0
XS Output Increment= 10
Write Gradation File= 0
Read Gradation Hotstart= 0
Write HDF5 File= 1
Write Binary Output= 1
Write DSS Sediment File= 0
SV Curve= 0
Specific Gage Flag= 0

--- KINCAIDRN.f01 (steady flow) ---

Flow Title=Flow
Program Version=5.07
Number of Profiles= 6
Profile Names=f1p,f10p,f4p,f2p,f02p,f1pplus
River Rch & RM=Kincaid Run,A2              ,1249
     523     275     367     442     731     773
Boundary for River Rch & Prof#=Kincaid Run,A2              , 1
Up Type= 0
Dn Type= 3
Dn Slope=0.038
Boundary for River Rch & Prof#=Kincaid Run,A2              , 2
Up Type= 0
Dn Type= 3
Dn Slope=0.038
Boundary for River Rch & Prof#=Kincaid Run,A2              , 3
Up Type= 0
Dn Type= 3
Dn Slope=0.038
Boundary for River Rch & Prof#=Kincaid Run,A2              , 4
Up Type= 0
Dn Type= 3
Dn Slope=0.038
Boundary for River Rch & Prof#=Kincaid Run,A2              , 5
Up Type= 0
Dn Type= 3
Dn Slope=0.038
Boundary for River Rch & Prof#=Kincaid Run,A2              , 6
Up Type= 0
Dn Type= 3
Dn Slope=0.038
DSS Import GetInterval= 0
DSS Import GetPeak= 0
DSS Import FillOption= 0

--- KINCAIDRN.g02 (geometry) ---

Geom Title=Kincaid Run
Program Version=5.07

River Reach=Kincaid Run     ,A2
Reach XY= 30
2181593.89951831370832.1311017272181574.13873105370834.949009478
2181550.18011755370830.8459993152181498.63166422370835.375189722
2181488.93056814370840.4634341452181472.87941913370852.863671809
2181447.38603181370878.7451817242181437.22036973370886.053237975
2181381.95801306370904.6083189852181346.55454056370908.898992807
 2181327.7563498 370920.369114222181306.18913572370924.301192984
 2181236.6384218370930.361876398 2181218.6561743370927.354008392
2181197.34224056370921.0643228142181173.65954514370918.481650814
2181052.89863181370908.1010941422181025.74350239370911.034487233
2180997.08115813370921.3015270532180887.68866038370974.259098306
2180865.60701163370987.4802004842180848.09621988370991.412607312
2180792.18983564370978.4841554762180731.48129563 370949.43237631
2180665.81508839370929.7880586392180608.54256514370919.475087151
2180547.37470847370921.2555954012180513.25404181370917.315314561
2180478.06677622370904.7539879832180413.82248214370868.612656057

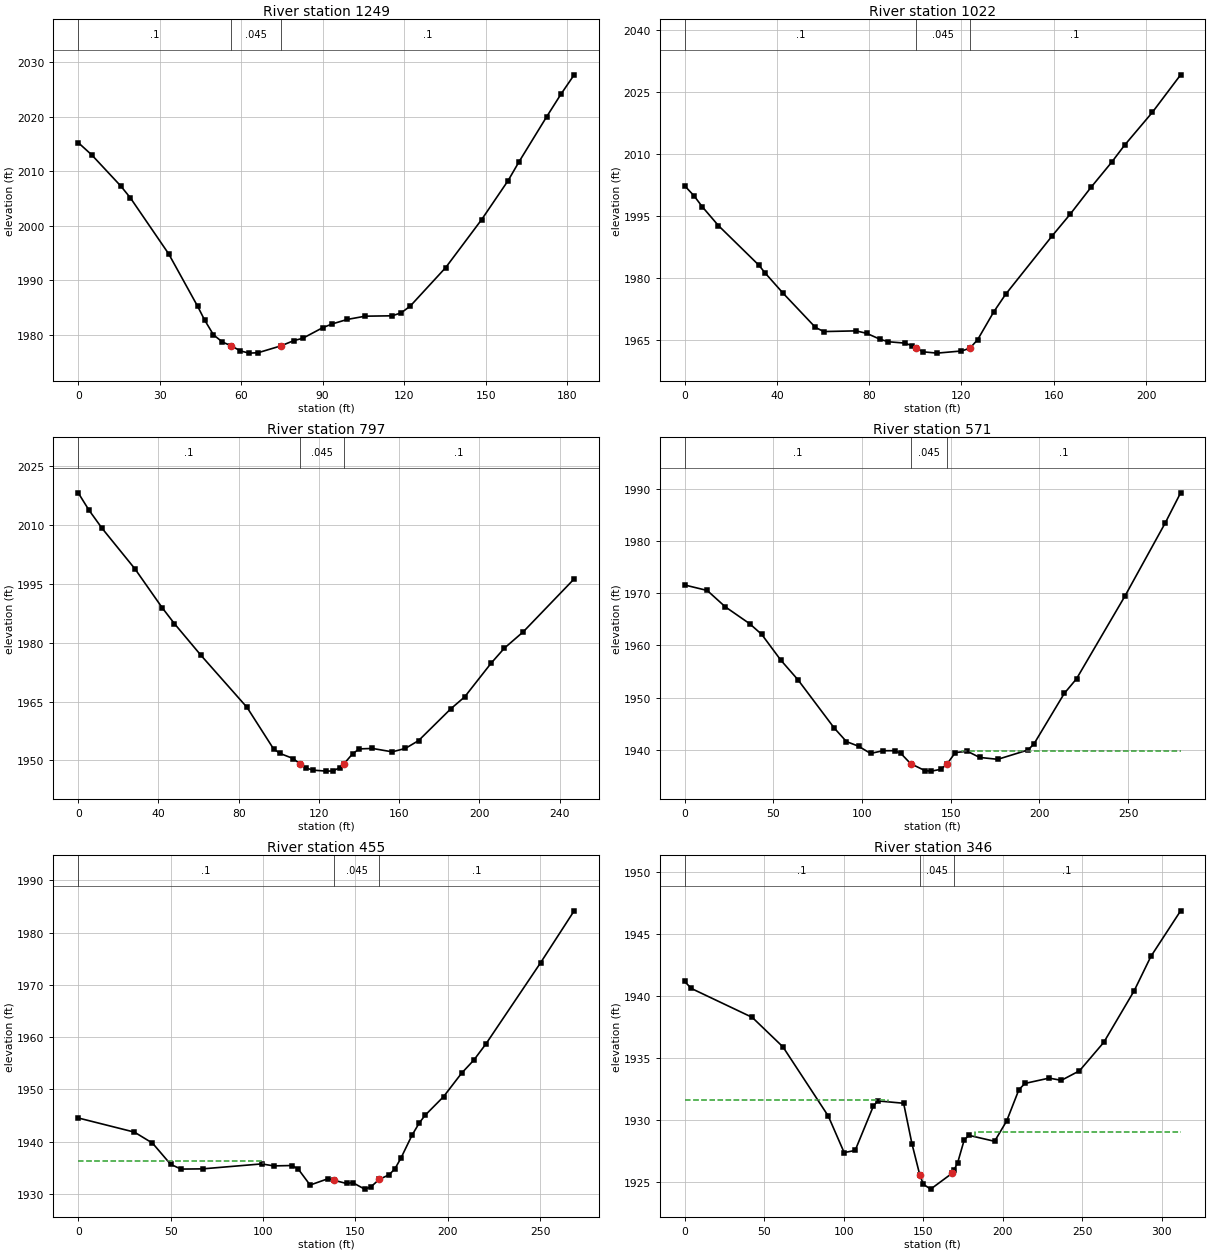
Type RM Length L Ch R = 1 ,1249    ,226.6,226.6,226.6
XS GIS Cut Line= 2
2181595.35316856370766.5668956522181582.44282077370948.746247798
#Sta/Elev= 30
       0 2015.23       5 2012.97    15.7 2007.27    19.2 2005.12    33.3 1994.88
      44 1985.25    46.5  1982.8    49.8 1980.06    53.1 1978.74    56.4 1978.03
    59.7 1977.12    62.9 1976.71    66.2 1976.78    74.61978.033    79.4    1979
    82.7 1979.43      90 1981.36    93.5 1982.05    99.1 1982.88   105.7 1983.47
   115.6 1983.54   118.9 1984.08   122.2 1985.29   135.3 1992.36   148.5 2001.12
   158.3 2008.29   162.3 2011.72   172.5 2019.98   177.7 2024.06   182.6 2027.63
#Mann= 3 ,-1 , 0
       0      .1       0    56.4    .045       0    74.6      .1       0
Bank Sta=56.4,74.6
XS Rating Curve= 0 ,0
Exp/Cntr=0.3,0.1

Type RM Length L Ch R = 1 ,1022    ,225.7,225.7,225.7
XS GIS Cut Line= 5
 2181348.3060594370802.598911712 2181348.3060594370802.598911712
2181386.65668409370903.0306775852181425.00730878371003.462443457
2181425.00730878371003.462443457
#Sta/Elev= 30
       0 2002.29     4.1 1999.84     7.6 1997.23    14.6 1992.66    32.2 1983.02
    34.9 1981.13    42.7 1976.22    56.7 1967.94    60.3 1966.94    74.3 1967.11
    78.9 1966.51    84.8 1965.05    88.3 1964.47    95.4 1964.14    98.5 1963.52
   100.31962.857   103.5 1962.02   109.4 1961.71     120 1962.23   123.61962.877
     127 1964.97     134 1971.73   139.1 1975.95   159.4 1990.21   167.1 1995.39
   176.1 2001.89   185.1 2008.01   190.7 2012.14   202.7 2020.08     215 2029.21
#Mann= 3 ,-1 , 0
       0      .1       0   100.3    .045       0   123.6      .1       0
Bank Sta=100.3,123.6
XS Rating Curve= 0 ,0
Exp/Cntr=0.3,0.1

Type RM Length L Ch R = 1 ,797     ,225.4,225.4,225.4
XS GIS Cut Line= 5
2181175.45775746370794.5443553012181175.45775746370794.544355301
2181167.07037438370917.915247789 2181158.6829913371041.286140278
 2181158.6829913371041.286140278
#Sta/Elev= 30
       0 2018.27     5.3  2013.9    11.9 2009.21    28.3 1998.86    41.9 1988.93
      48 1984.87    61.2 1976.81    84.2  1963.5    97.4 1952.93   100.7 1951.75
   107.2 1950.46   110.71949.035   113.8 1948.02   117.1  1947.5   123.7 1947.25
     127 1947.29   130.3  1948.1   132.41949.058   136.8 1951.65   140.1 1952.92
   146.7 1953.04   156.6 1952.17   163.1 1953.04   169.7 1955.03   185.8 1963.16
   192.7 1966.19   205.9  1974.8   212.5 1978.63   221.9 1982.79   247.3  1996.3
#Mann= 3 ,-1 , 0
       0      .1       0   110.7    .045       0   132.4      .1       0
Bank Sta=110.7,132.4
XS Rating Curve= 0 ,0
Exp/Cntr=0.3,0.1

Type RM Length L Ch R = 1 ,571     ,116.1,116.1,116.1
XS GIS Cut Line= 5
2180911.50808114370810.6008734432180911.50808114370810.600873443
2180949.98260373370945.0090006692180988.45712633371079.417127895
2180988.45712633371079.417127895
#Sta/Elev= 30
       0 1971.56    12.7 1970.51    22.9 1967.38    36.6 1964.16    43.4 1962.12
    54.2 1957.18    63.9 1953.41    84.3  1944.2    91.2  1941.6      98 1940.72
   104.8 1939.33   111.7 1939.85   118.5 1939.86   121.9 1939.33   127.41937.377
   135.5 1936.04     139 1935.95   144.4 1936.29     1481937.354   152.6 1939.51
   159.4 1939.74   166.3 1938.57   176.5 1938.21   193.6    1940     197  1941.2
     214 1950.81   220.9 1953.61   248.2 1969.43   270.9 1983.41   279.6 1989.19
#Mann= 3 ,-1 , 0
       0      .1       0   127.4    .045       0     148      .1       0
#XS Ineff= 2 , 0
                          156.31         1939.84
Permanent Ineff=
       F       F
Bank Sta=127.4,148
XS Rating Curve= 0 ,0
Exp/Cntr=0.3,0.1

Type RM Length L Ch R = 1 ,455     ,109.5,109.5,109.5
XS GIS Cut Line= 2
2180846.65932094370838.3796410842180843.17352704371106.785771637
#Sta/Elev= 30
       0 1944.51    30.4  1941.8    40.2 1939.69      50 1935.64    55.6 1934.72
    67.3 1934.76    99.3 1935.71   105.8 1935.33   115.7  1935.4   119.1 1934.71
   125.5 1931.66   135.3 1932.89   138.5 1932.57   145.2 1931.96   148.5 1932.14
     155 1930.88   158.3 1931.28   162.91932.748   168.2 1933.62   171.4 1934.77
   174.7 1936.85   180.6 1941.17   184.6 1943.57   187.8 1945.05   197.7 1948.58
   207.5 1953.09   214.1 1955.59   220.7 1958.71   250.2 1974.22   268.4 1984.18
#Mann= 3 , 0 , 0
       0      .1       0   138.5    .045       0   162.9      .1       0
#XS Ineff= 2 , 0
             100 1936.28
Permanent Ineff=
       F       F
Bank Sta=138.5,162.9
XS Rating Curve= 0 ,0
Exp/Cntr=0.3,0.1

Type RM Length L Ch R = 1 ,346     ,115,115,115
XS GIS Cut Line= 2
2180820.73230117370822.5117360752180661.50467843371090.760073487
#Sta/Elev= 30
       0 1941.17     4.1 1940.61    42.5 1938.27    61.8 1935.89    90.3 1930.31
   100.3 1927.36   107.2 1927.53   118.6 1931.09   121.4 1931.53   137.7 1931.34
   142.9 1928.09   147.81925.587   150.1  1924.8   154.7 1924.41   168.2 1925.69
   169.3 1925.92   171.7 1926.55   175.8 1928.38   178.8 1928.75   194.9 1928.27
   202.5 1929.91   210.2 1932.44     214 1932.94   229.2 1933.37   236.9 1933.19
   248.3 1933.96   263.6 1936.26   282.7 1940.42   293.2 1943.19   311.9 1946.87
#Mann= 3 ,-1 , 0
       0      .1       0   147.8    .045       0   169.3      .1       0
#XS Ineff= 2 , 0
           127.7 1931.62  182.88         1929.01
Permanent Ineff=
       F       F
Bank Sta=147.8,168.2
XS Rating Curve= 0 ,0
Exp/Cntr=0.3,0.1

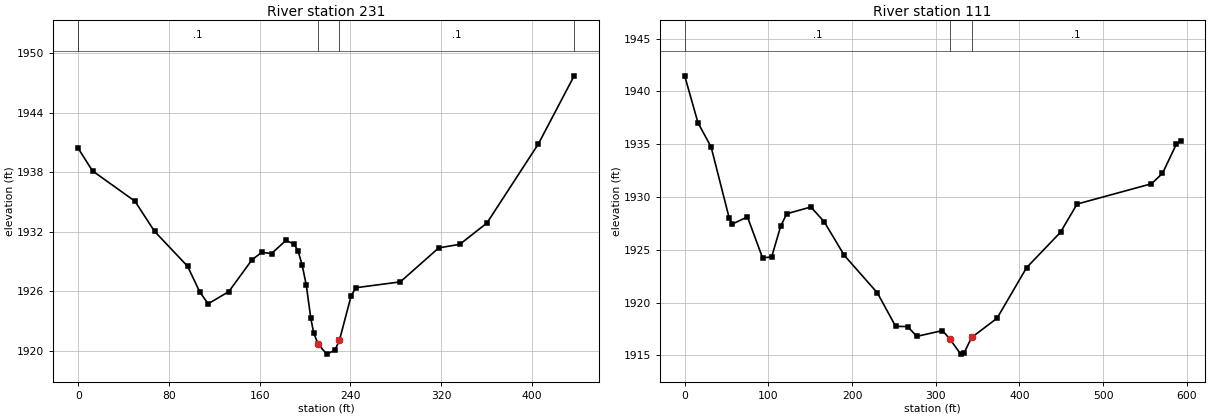
Type RM Length L Ch R = 1 ,231     ,119.8,119.8,119.8
XS GIS Cut Line= 4
 2180807.1536567370803.5217020512180652.61679366370877.885305321
2180606.13954161370980.1352598182180613.11112942371133.510191563
#Sta/Elev= 30
       0 1940.41    12.6 1938.14      50 1935.08    67.3 1932.04    96.4 1928.52
   107.3  1925.9   114.6 1924.73   132.8 1925.96   153.3 1929.18   161.9 1929.92
   170.5  1929.8   183.1 1931.12   190.3 1930.75   193.9 1930.06   197.5 1928.61
   201.1 1926.62   205.1 1923.26   207.6  1921.8   211.51920.669   219.1 1919.65
   226.3 1920.04   230.31921.036   240.7 1925.55   244.8 1926.35     284 1926.94
   317.9 1930.37   336.5 1930.73   360.4 1932.88   405.8 1940.87   437.3 1947.73
#Mann= 5 ,-1 , 0
       0      .1       0       0      .1       0   211.5    .045       0
   230.3      .1       0   437.1      .1       0
Bank Sta=211.5,230.3
XS Rating Curve= 0 ,0
Exp/Cntr=0.3,0.1

Type RM Length L Ch R = 1 ,111     ,111,111,111
XS GIS Cut Line= 4
2180798.23287519 370764.80447195 2180529.4212484370888.709831174
2180497.21985561370944.7122534222180517.52073368371175.722245194
#Sta/Elev= 30
       0 1941.47    15.9 1937.02    31.6 1934.73    53.3 1927.97    56.9 1927.44
      75 1928.11      93 1924.24   103.9 1924.32   114.7 1927.23   121.9 1928.41
   150.8 1929.05   166.7 1927.65   190.6 1924.48   230.3 1920.91     252 1917.75
   266.4 1917.73   277.3  1916.8     308 1917.35     317 1916.53   329.7 1915.12
   333.5 1915.18   342.81916.697   373.2 1918.52   408.5 1923.31     449 1926.66
   468.8 1929.33   557.7 1931.25   570.8 1932.23   587.3 1934.98   592.5 1935.26
#Mann= 3 , 0 , 0
       0      .1       0     317    .045       0   342.8      .1       0
Bank Sta=317,342.8
XS Rating Curve= 0 ,0
Exp/Cntr(USF)=0,0
Exp/Cntr=0.3,0.1
LCMann Table=0

Chan Stop Cuts=-1
Use User Specified Reach Order=0
Composite Channel Slope=5